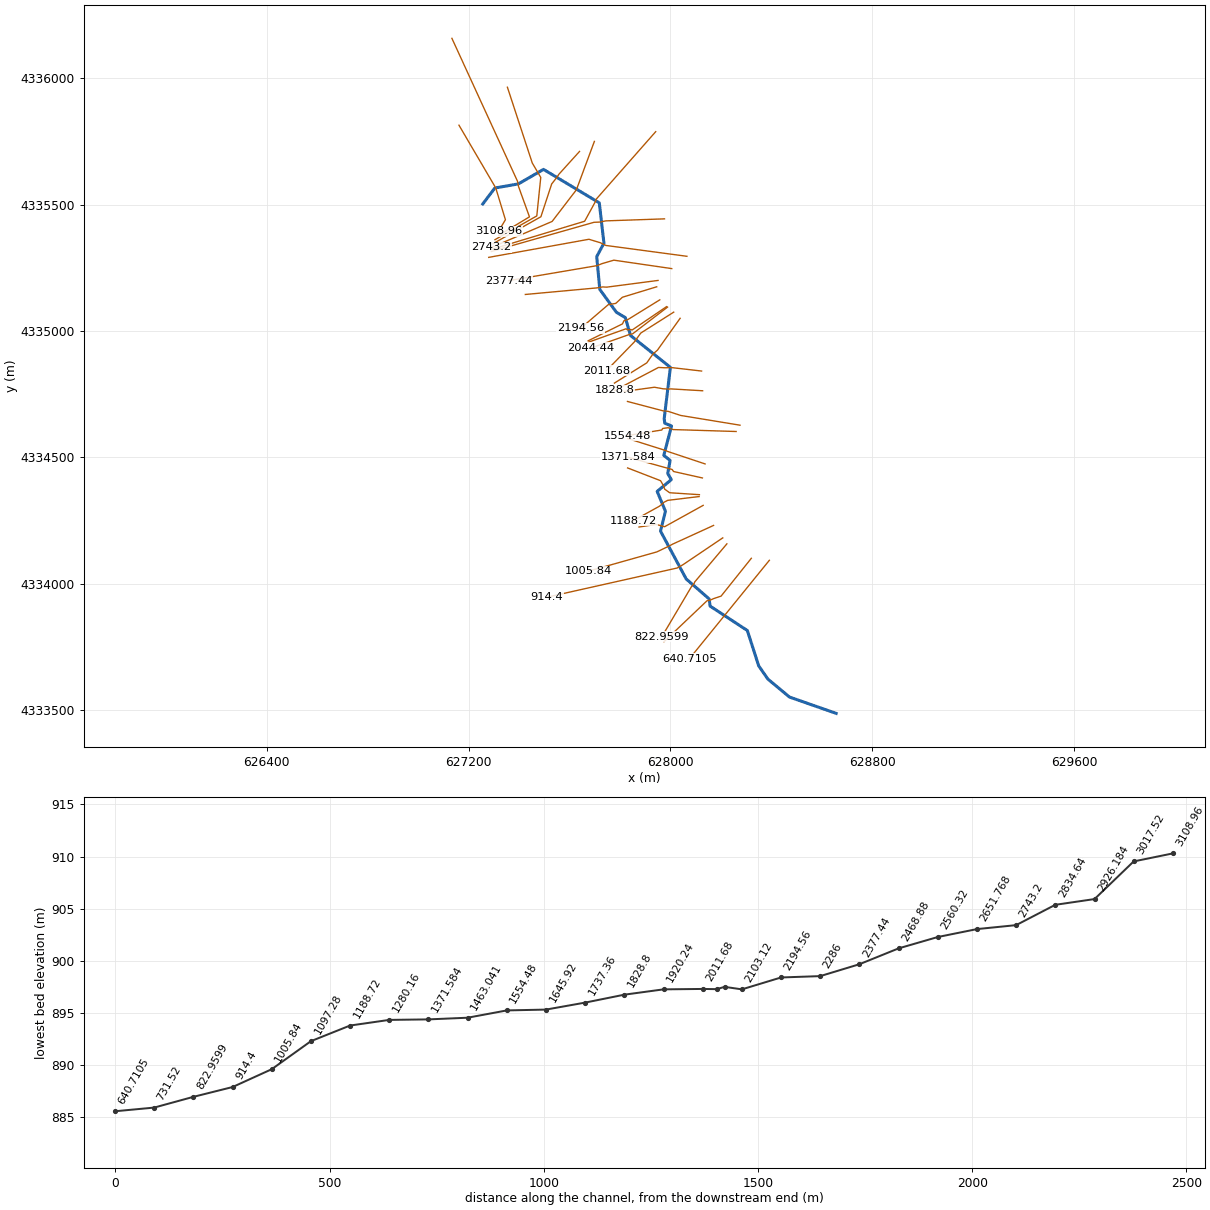
--- SnyderRun.prj (project) ---

Proj Title=SnyderRun
Current Plan=p01
Default Exp/Contr=0.3,0.1
SI Units
Geom File=g01
Flow File=f01
Plan File=p01
Y Axis Title=Elevation
X Axis Title(PF)=Main Channel Distance
X Axis Title(XS)=Station
BEGIN DESCRIPTION:
September 2018
Tucker County ABFE Study
US Army Corps of Engineers, Pittsburgh District
NAD 1983 UTM 17N (meters)
END DESCRIPTION:
DSS Export Rating Curves= 0
DSS Export Rating Curve Sorted= 0
DSS Export Volume Flow Curves= 0
DXF OffsetX= 0
DXF OffsetY= 0
DXF ScaleX= 1
DXF ScaleY= 10

--- SnyderRun.p01 (plan) ---

Plan Title=SnyderRun_plan
Program Version=5.05
Short Identifier=Plan1_subcritical
Geom File=g01
Flow File=f01
Subcritical Flow
K Sum by GR= 0
Std Step Tol= 0.003
Critical Tol= 0.003
Num of Std Step Trials= 20
Max Error Tol= 0.1
Flow Tol Ratio= 0.001
Split Flow NTrial= 30
Split Flow Tol= 0.006
Split Flow Ratio= 0.02
Log Output Level= 0
Friction Slope Method= 1
Unsteady Friction Slope Method= 2
Unsteady Bridges Friction Slope Method= 1
Parabolic Critical Depth
Global Vel Dist= 0 , 0 , 0
Global Log Level= 0
CheckData=True
Encroach Param=-1 ,0,0, 0
Computation Interval=1MIN
Output Interval=1HOUR
Instantaneous Interval=1HOUR
Mapping Interval=1HOUR
Computation Time Step Use Courant=        0
Computation Time Step Use Time Series=    0
Computation Time Step Count To Double=0
Computation Time Step Max Doubling=0
Computation Time Step Max Halving=0
Computation Time Step Residence Courant=0
Run HTab= 0
Run UNet= 0
Run Sediment= 0
Run PostProcess= 0
Run WQNet= 0
Run RASMapper=-1
UNET Theta= 1
UNET Theta Warmup= 1
UNET ZTol= 0.006
UNET ZSATol= 0.006
UNET MxIter= 20
UNET Max Iter WO Improvement= 0
UNET MaxInSteps= 0
UNET DtIC= 0
UNET DtMin= 0
UNET MaxCRTS= 20
UNET WFStab= 2
UNET SFStab= 1
UNET WFX= 1
UNET SFX= 1
UNET 1D Methodology=Finite Difference
UNET DSS MLevel= 4
UNET Pardiso=0
UNET DZMax Abort= 30
UNET Use Existing IB Tables=-1
UNET Froude Reduction=False
UNET Froude Limit= 0.8
UNET Froude Power= 4
UNET D1 Cores= 0
UNET D2 Coriolis=0
UNET D2 Cores= 0
UNET D2 Theta= 1
UNET D2 Theta Warmup= 1
UNET D2 Z Tol= 0.003
UNET D2 Volume Tol= 0.003
UNET D2 Max Iterations= 20
UNET D2 Equation= 0
UNET D2 RampUpFraction=0.1
UNET D2 TimeSlices= 1
UNET D2 BCVolumeCheck=0
UNET D1D2 MaxIter= 0
UNET D1D2 ZTol=0.003
UNET D1D2 QTol=0.1
UNET D1D2 MinQTol=0.03
Write IC File= 0
Write IC File at Fixed DateTime=0
Write IC File at Sim End=0
Echo Input=False
Echo Parameters=False
Echo Output=False
Write Detailed= 0
HDF Write Warmup=0
HDF Write Time Slices=0
HDF Flush=0
HDF Face Node Velocities=0
HDF Compression= 1
HDF Chunk Size= 1
HDF Spatial Parts= 1
HDF Use Max Rows=0
HDF Fixed Rows= 1
Calibration Method= 0
Calibration Iterations= 20
Calibration Max Change=0.05
Calibration Tolerance=0.2
Calibration Maximum=1.5
Calibration Minimum=0.5
Calibration Optimization Method= 1
WQ AD Non Conservative
WQ ULTIMATE=-1
WQ Max Comp Step=1HOUR
WQ Output Interval=15MIN
WQ Output Selected Increments= 0
WQ Output face flow=0
WQ Output face velocity=0
WQ Output face area=0
WQ Output face dispersion=0
WQ Output cell volume=0
WQ Output cell surface area=0
WQ Output cell continuity=0
WQ Output cumulative cell continuity=0
WQ Output face conc=0
WQ Output face dconc_dx=0
WQ Output face courant=0
WQ Output face peclet=0
WQ Output face adv mass=0
WQ Output face disp mass=0
WQ Output cell mass=0
WQ Output cell source sink temp=0
WQ Output nsm pathways=0
WQ Output nsm derived pathways=0
WQ Output MaxMinRange=-1
WQ Daily Max Min Mean=-1
WQ Daily Range=0
WQ Daily Time=0
WQ Create Restart=0
WQ Fixed Restart=0
WQ System Summary=0
WQ Write To DSS=0
WQ Use Fixed Temperature=0
Sorting and Armoring Iterations= 10
XS Update Threshold= 0.02
Bed Roughness Predictor= 0
Hydraulics Update Threshold= 0.02
Energy Slope Method= 1
Volume Change Method= 1
Sediment Retention Method= 0
XS Weighting Method= 0
Number of US Weighted Cross Sections= 1
Number of DS Weighted Cross Sections= 1
Upstream XS Weight=0
Main XS Weight=1
Downstream XS Weight=0
Number of DS XS's Weighted with US Boundary= 1
Upstream Boundary Weight= 1
Weight of XSs Associated with US Boundary= 0
Number of US XS's Weighted with DS Boundary= 1
Downstream Boundary Weight= 0.5
Weight of XSs Associated with DS Boundary= 0.5
Percentile Method= 0
Sediment Output Level= 4
Mass or Volume Output= 0
Output Increment Type= 1
Profile and TS Output Increment= 1
XS Output Flag= 0
XS Output Increment= 10
Write Gradation File= 0
Read Gradation Hotstart= 0
Write HDF5 File= 1
Write Binary Output= 1
Write DSS Sediment File= 0
SV Curve= 0
Specific Gage Flag= 0

--- SnyderRun.f01 (steady flow) ---

Flow Title=SnyderRun_flow
Program Version=5.05
Number of Profiles= 1
Profile Names=PF 1
River Rch & RM=Snyder Run,1               ,3108.96
   13.25
River Rch & RM=Snyder Run,1               ,2651.768
    19.4
River Rch & RM=Snyder Run,1               ,2286
   21.75
River Rch & RM=Snyder Run,1               ,1554.48
   23.59
River Rch & RM=Snyder Run,1               ,822.9599
   27.92
River Rch & RM=Snyder Run,1               ,548.64
    28.2
River Rch & RM=Snyder Run,1               ,91.50916
   29.44
Boundary for River Rch & Prof#=Snyder Run,1               , 1
Up Type= 2
Dn Type= 1
Dn Known WS=877.7
DSS Import GetInterval= 0
DSS Import GetPeak= 0
DSS Import FillOption= 0

--- SnyderRun.g01 (geometry) ---

Geom Title=SnyderRun_geometry
Program Version=5.05

River Reach=Snyder Run      ,1
Reach XY= 30
     627256.4914     4335503.289     627304.1165    4335566.3923
     627397.3824    4335582.6642     627496.9982    4335640.2112
      627718.058    4335507.6546     627736.3804    4335348.1106
     627707.8054    4335294.9292     627719.9762    4335165.0185
     627785.9227    4335074.4964     627821.3118    4335053.3641
     627841.6848    4334982.7203     627999.6414    4334856.7783
     627975.0351    4334653.0488     627977.6809    4334635.3216
     628004.1393    4334624.7383     627973.5206    4334508.2299
      627998.583     4334488.213      627989.058    4334436.6192
     628003.3455    4334412.2774     627947.2538    4334365.7107
     627980.0579    4334286.9977      627960.483    4334208.5479
     628062.3477    4334019.1058        628153.1    4333940.2598
     628157.0688    4333911.6848      628304.442    4333815.1117
     628349.4212    4333675.4114     628385.6692    4333623.0238
     628471.3944    4333551.8507     628656.4569     4333487.204

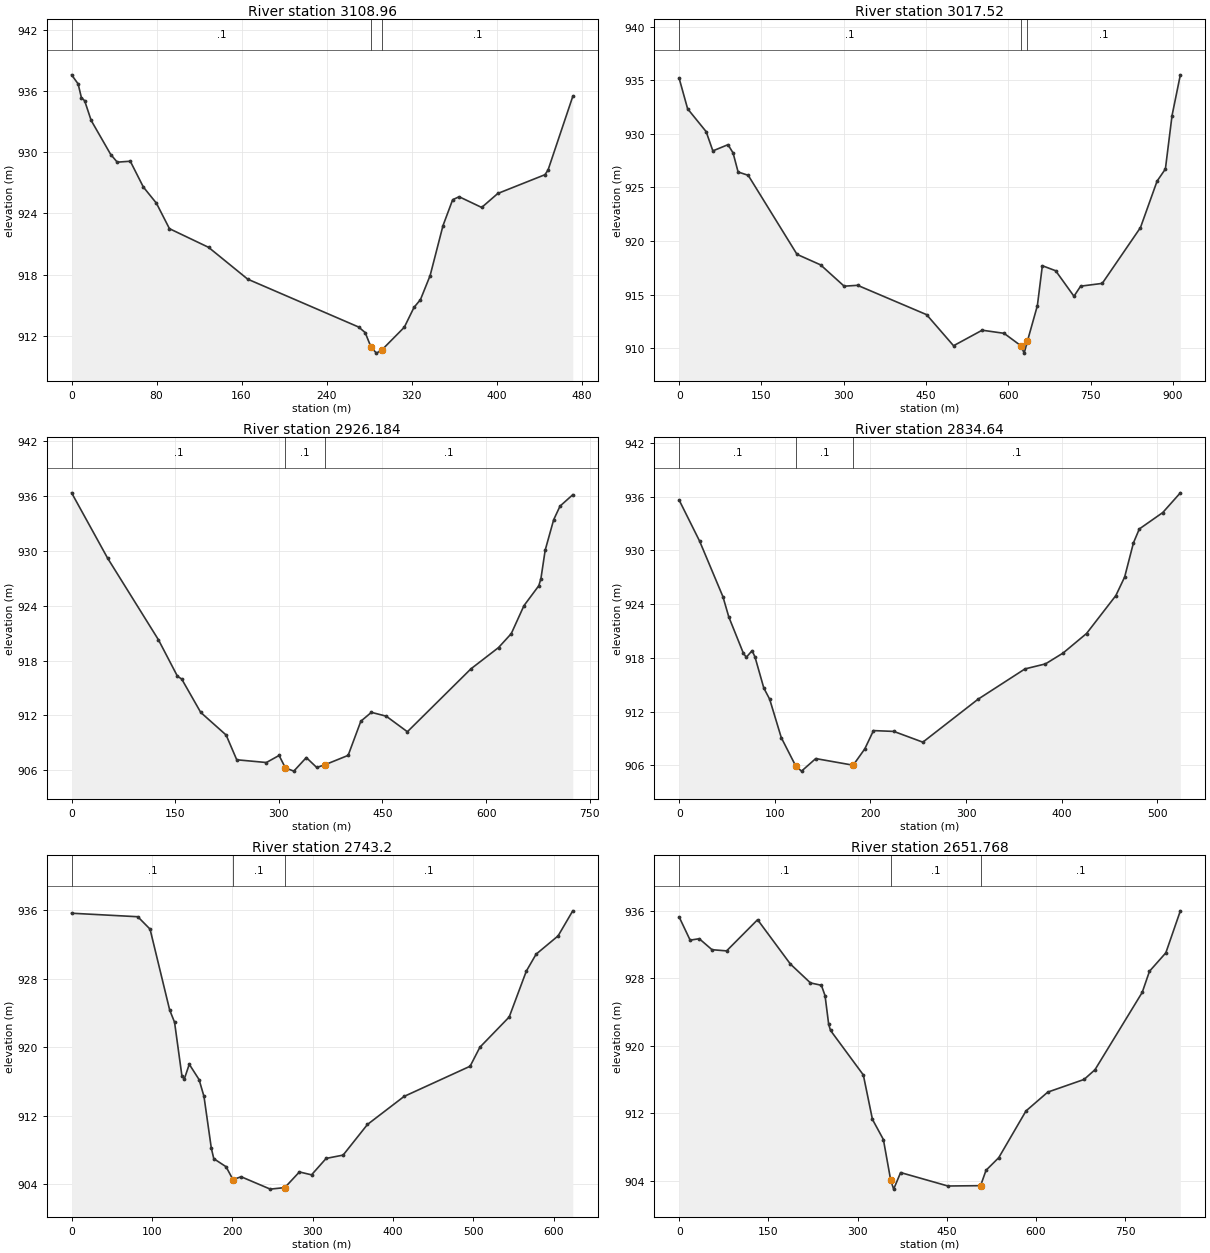
Type RM Length L Ch R = 1 ,3108.96 ,93.44,91.44,90.39
XS GIS Cut Line= 5
     627162.0976    4335815.0608      627303.507    4335574.0958
     627308.9993    4335562.7878     627346.1666    4335440.8692
     627319.2604      4335395.96
#Sta/Elev= 30
       0  937.58    6.14  936.69    9.21  935.35   12.28  935.04   18.42  933.11
   36.84  929.77   42.98  929.02   55.26  929.11   67.55  926.58   79.83     925
   92.11   922.5  128.95  920.67  165.79  917.55  270.18  912.86  276.32  912.32
  281.91  910.88  286.94   910.3  291.96   910.6  313.21  912.84  322.31  914.78
  328.38  915.54  337.49   917.9  349.62   922.8  358.73  925.34   364.8  925.63
  386.04  924.58  401.21  925.95   445.6  927.79  448.51  928.25  471.77  935.46
#Mann= 3 , 0 , 0
       0      .1       0  281.91      .1       0  291.96      .1       0
Bank Sta=281.91,291.96
XS Rating Curve= 0 ,0
Exp/Cntr=0.3,0.1

Type RM Length L Ch R = 1 ,3017.52 ,86.7,91.34,96.05
XS GIS Cut Line= 5
     627134.1575    4336158.8081     627394.2317    4335592.6728
     627398.1537    4335572.0768     627441.3985    4335452.2513
     627319.3662    4335378.8149
#Sta/Elev= 30
       0  935.17   15.35  932.34    49.1  930.21   61.38  928.41      89  928.99
   98.21  928.22  107.42  926.44  125.83  926.13  214.83  918.75   257.8  917.77
  300.77  915.78  325.32  915.86  451.15  913.12  500.25  910.22  552.43  911.67
  592.32  911.38  623.02  910.22  629.01  909.53     635  910.66  653.08  913.96
  662.18  917.69  686.44  917.22  719.81  914.84  731.94  915.78  771.37  916.04
  841.07  921.25  871.37  925.59  886.52  926.72  898.64  931.71   913.8  935.51
#Mann= 3 , 0 , 0
       0      .1       0  623.02      .1       0     635      .1       0
Bank Sta=623.02,635
XS Rating Curve= 0 ,0
Exp/Cntr=0.3,0.1

Type RM Length L Ch R = 1 ,2926.184,106.33,91.54,78.84
XS GIS Cut Line= 5
     627354.0267    4335965.2651     627452.4896    4335665.3883
     627486.0995    4335608.2606     627470.4062     4335455.953
     627304.8141    4335362.0138
#Sta/Elev= 30
       0  936.31   52.09  929.18  125.64  920.27  153.22  916.28  159.35  915.98
  186.93  912.33   223.7  909.86  239.02  907.16  281.92  906.86  300.31  907.63
   309.5  906.27  321.65  905.92  339.73   907.4  354.79  906.32  366.85  906.62
  400.28  907.64  418.66  911.37  433.97  912.34   455.4  911.92  486.03  910.22
  578.01  917.09  617.93  919.41  636.36  920.93  654.78  923.99  676.27  926.17
  679.34  926.95  685.49  930.05  697.77  933.37  706.98  934.86   725.4   936.1
#Mann= 3 , 0 , 0
       0      .1       0   309.5      .1       0  366.85      .1       0
Bank Sta=309.5,366.85
XS Rating Curve= 0 ,0
Exp/Cntr=0.3,0.1

Type RM Length L Ch R = 1 ,2834.64 ,88.84,91.44,91.46
XS GIS Cut Line= 6
     627639.7773    4335711.2645     627557.8806    4335620.7858
     627549.7538    4335608.4726     627529.4027    4335582.4866
     627486.7089    4335452.7213     627296.8766    4335346.1388
#Sta/Elev= 30
       0  935.59   21.36  931.02   45.76  924.82   51.87  922.57   67.12  918.52
   70.17  918.07   76.27  918.81   79.33  918.08   88.48  914.64   94.58   913.4
  106.78   909.1  122.04  905.91  127.94  905.37  142.79  906.77  181.94  906.03
  194.08  907.85  203.19  909.89  224.44   909.8   254.8   908.6  312.54  913.39
   361.6  916.77  383.06  917.33  401.46  918.54  425.99  920.72  456.65  924.95
  465.85  927.02  475.05  930.83  481.19  932.38  505.72  934.21  524.11  936.41
#Mann= 3 , 0 , 0
       0      .1       0  122.04      .1       0  181.94      .1       0
Bank Sta=122.04,181.94
XS Rating Curve= 0 ,0
Exp/Cntr=0.3,0.1

Type RM Length L Ch R = 1 ,2743.2  ,91.11,91.43,92.35
XS GIS Cut Line= 5
     627698.5149    4335750.9521     627629.4174    4335565.0071
     627623.1869    4335554.0121      627531.092    4335434.0879
     627290.5266    4335331.1104
#Sta/Elev= 30
       0  935.68    82.4  935.27   97.66  933.82  122.07  924.37  128.18  922.93
  137.33  916.66  140.38  916.31  146.49  918.02  158.69  916.23   164.8  914.26
  173.95   908.2  177.01  906.98  192.26  906.04   200.9  904.53  211.01  904.87
   247.3  903.42  265.44   903.6  283.59  905.43  298.71  905.09  316.85  907.01
  338.02   907.4   368.3  910.98  413.94  914.26   496.1  917.79  508.27  920.01
  544.78  923.55  566.08  928.91  578.25  930.89  605.64  933.03  623.89  935.96
#Mann= 3 , 0 , 0
       0      .1       0   200.9      .1       0  265.44      .1       0
Bank Sta=200.9,265.44
XS Rating Curve= 0 ,0
Exp/Cntr=0.3,0.1

Type RM Length L Ch R = 1 ,2651.768,103.32,91.45,77.66
XS GIS Cut Line= 5
     627941.4029    4335789.3697     627706.0543    4335522.5297
     627704.0753    4335515.2761     627659.8857    4335434.8273
     627288.4099    4335322.6438
#Sta/Elev= 30
       0  935.23    18.4   932.5   33.74  932.67   55.21  931.37   79.75  931.23
  131.89  934.92   187.1  929.67  220.84  927.44  239.24  927.16  245.38  925.93
  251.51  922.53  254.58  921.82  309.79  916.55  325.13  911.29  343.53  908.91
   355.8  904.11  360.81  903.04   372.5     905  452.04  903.41  507.05  903.45
  516.21  905.27   537.6  906.76  583.43  912.29   620.1  914.52  681.21  916.02
  699.54  917.17  778.98  926.32  791.21  928.82  818.71     931  843.15  935.97
#Mann= 3 , 0 , 0
       0      .1       0   355.8      .1       0  507.05      .1       0
Bank Sta=355.8,507.05
XS Rating Curve= 0 ,0
Exp/Cntr=0.3,0.1

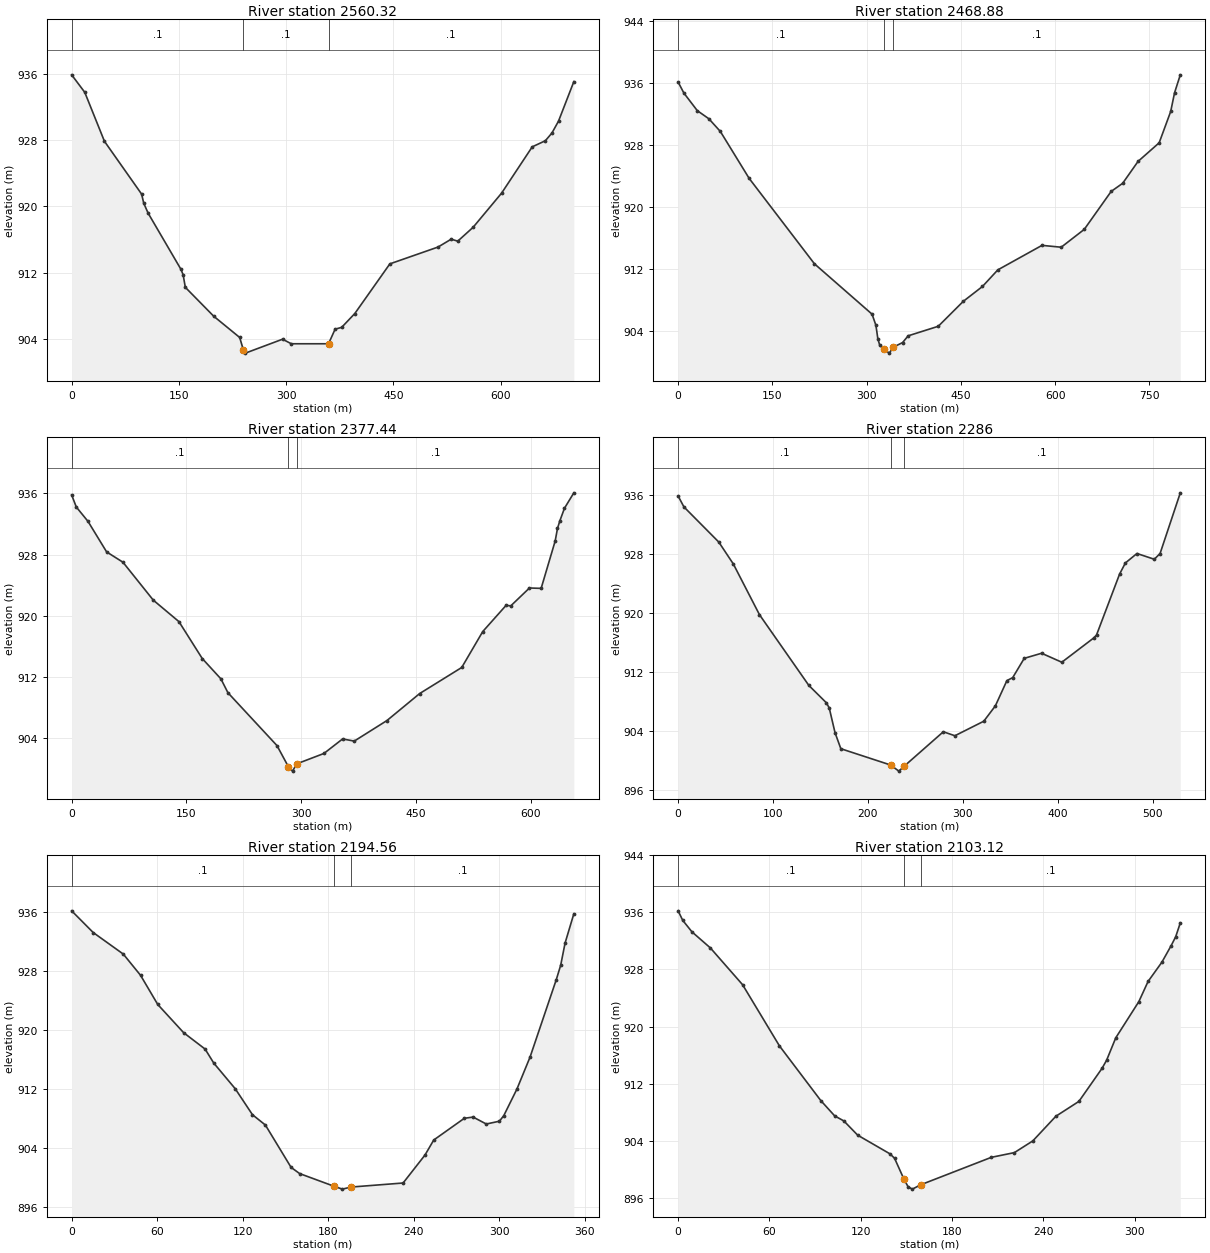
Type RM Length L Ch R = 1 ,2560.32 ,99.14,91.44,78.73
XS GIS Cut Line= 6
      627976.328    4335444.3523     627744.0221    4335436.3971
     627730.8329    4335433.8404     627722.2733    4335431.6346
     627697.2962    4335430.7917     627290.5266    4335315.2354
#Sta/Elev= 30
       0  935.86   18.35  933.75   45.88  927.84   97.87  921.47  100.93  920.35
  107.05  919.16  152.92  912.39  155.98  911.73  159.04  910.22   198.8  906.73
  235.09  904.17  240.39  902.62  243.04  902.28  295.05  903.96   307.3  903.41
   359.4  903.41  368.59  905.17  377.78  905.39  396.17  907.06  445.19  913.05
  512.61  915.08  530.99  916.03  540.19  915.79  561.64  917.46  601.47  921.58
  644.37  927.17  662.76  927.91  671.95  928.84  681.14  930.27  702.59  935.04
#Mann= 3 , 0 , 0
       0      .1       0  240.39      .1       0   359.4      .1       0
Bank Sta=240.39,359.4
XS Rating Curve= 0 ,0
Exp/Cntr=0.3,0.1

Type RM Length L Ch R = 1 ,2468.88 ,73.25,91.44,102.71
XS GIS Cut Line= 5
     628065.2281    4335296.1854     627744.1919    4335339.0962
     627722.2486    4335349.7911     627676.9977    4335363.6043
     627279.9432     4335291.952
#Sta/Elev= 30
       0  936.13    9.17  934.71   30.56  932.44   48.89   931.4   67.22  929.76
  113.06  923.71  216.95   912.7  308.61  906.21  314.72  904.78  317.78  903.06
  320.84   902.2  326.94  901.72   336.1  901.19   342.2  901.95  357.17  902.55
  366.04  903.42  413.95  904.65  453.69  907.86  484.26  909.78  508.71  911.92
  579.01  915.08  609.57  914.84  646.25  917.14  689.05  922.03  707.38  923.08
  731.84   925.9  765.46   928.3   783.8  932.34  789.91  934.74  799.08  937.06
#Mann= 3 , 0 , 0
       0      .1       0  326.94      .1       0   342.2      .1       0
Bank Sta=326.94,342.2
XS Rating Curve= 0 ,0
Exp/Cntr=0.3,0.1

Type RM Length L Ch R = 1 ,2377.44 ,97.08,91.44,86.97
XS GIS Cut Line= 5
      628004.903    4335247.5019     627775.6984    4335280.8801
     627728.7488    4335267.0948     627708.6507    4335259.1313
      627359.583    4335199.8769
#Sta/Elev= 30
       0   935.8     6.1  934.22   21.33  932.35   45.71  928.35   67.05     927
  106.67  922.04  140.19  919.23  170.67   914.4  195.05  911.74  204.19  909.93
  268.32  903.01  283.26  900.24  288.66  899.67  294.07  900.62  329.64  901.98
  354.06  903.88  369.32   903.6  412.05  906.29  454.78  909.82  509.73  913.23
   537.2  917.93  567.72  921.36  573.82  921.29  598.24  923.63   613.5  923.58
  631.82  929.77  634.87  931.42  637.92  932.41  644.02  934.07  656.23  936.08
#Mann= 3 , 0 , 0
       0      .1       0  283.26      .1       0  294.07      .1       0
Bank Sta=283.26,294.07
XS Rating Curve= 0 ,0
Exp/Cntr=0.3,0.1

Type RM Length L Ch R = 1 ,2286    ,84.28,91.44,87.42
XS GIS Cut Line= 6
     627950.8397    4335200.6706     627747.4495    4335174.0688
     627731.6009    4335174.9553     627717.3058    4335172.7561
     627710.0132    4335171.2792     627424.9793     4335145.108
#Sta/Elev= 30
       0  935.85    6.12  934.37   42.86   929.6   58.17  926.63   85.72  919.75
  137.77  910.15  156.14  907.81   159.2  907.11  165.32  903.75  171.45  901.57
  223.89  899.36  232.57  898.53  237.94  899.17  279.44  903.87  291.62  903.33
  322.07   905.3  334.25  907.38  346.43  910.81  352.52  911.21   364.7  913.83
  382.97  914.52  404.29   913.3  437.78  916.58  440.83  916.99  465.19  925.27
  471.28  926.77  483.46  928.05  501.73  927.27  507.82  928.05  529.13  936.28
#Mann= 3 , 0 , 0
       0      .1       0  223.89      .1       0  237.94      .1       0
Bank Sta=223.89,237.94
XS Rating Curve= 0 ,0
Exp/Cntr=0.3,0.1

Type RM Length L Ch R = 1 ,2194.56 ,86.77,91.44,94.89
XS GIS Cut Line= 5
      627945.548    4335175.5351     627809.6627    4335134.1731
     627783.2352     4335109.775     627753.5789    4335104.8323
     627643.9224    4335010.8317
#Sta/Elev= 30
       0  936.14   15.11   933.2   36.27  930.27   48.35   927.4   60.44  923.44
   78.58  919.62   93.69  917.39   99.73   915.5  114.84  912.01  126.93  908.49
     136  907.09  154.03  901.35  160.02  900.51  184.02   898.8  190.03   898.4
  196.05  898.68  232.66  899.23  248.02  903.02  254.17  905.06  275.68  908.01
  281.83  908.17  291.05  907.23  300.26  907.61  303.34  908.37  312.56  911.97
  321.78  916.31  340.21  926.82  343.29  928.77  346.36  931.77  352.51  935.74
#Mann= 3 , 0 , 0
       0      .1       0  184.02      .1       0  196.05      .1       0
Bank Sta=184.02,196.05
XS Rating Curve= 0 ,0
Exp/Cntr=0.3,0.1

Type RM Length L Ch R = 1 ,2103.12 ,47.19,40.26,29.86
XS GIS Cut Line= 5
     627957.6748    4335123.8531     627831.4776    4335045.9442
     627815.3525    4335040.8711      627809.804    4335028.6756
     627673.9086    4334961.7955
#Sta/Elev= 30
       0  936.21    3.03  934.88    9.08  933.27   21.19  931.02   42.37  925.87
   66.59  917.31   93.83  909.64  102.91  907.51  108.96   906.8  118.04  904.81
  139.23   902.2  142.26  901.58  148.31  898.71  151.13   897.6  153.94  897.26
  159.58  897.88  205.87  901.71  221.02  902.37  233.14  904.01  248.28  907.46
  263.43  909.54  278.58  914.15  281.61  915.29  287.66  918.44  302.81   923.5
  308.87  926.32  317.96  929.02  324.01  931.32  327.04  932.58  330.07  934.53
#Mann= 3 , 0 , 0
       0      .1       0  148.31      .1       0  159.58      .1       0
Bank Sta=148.31,159.58
XS Rating Curve= 0 ,0
Exp/Cntr=0.3,0.1

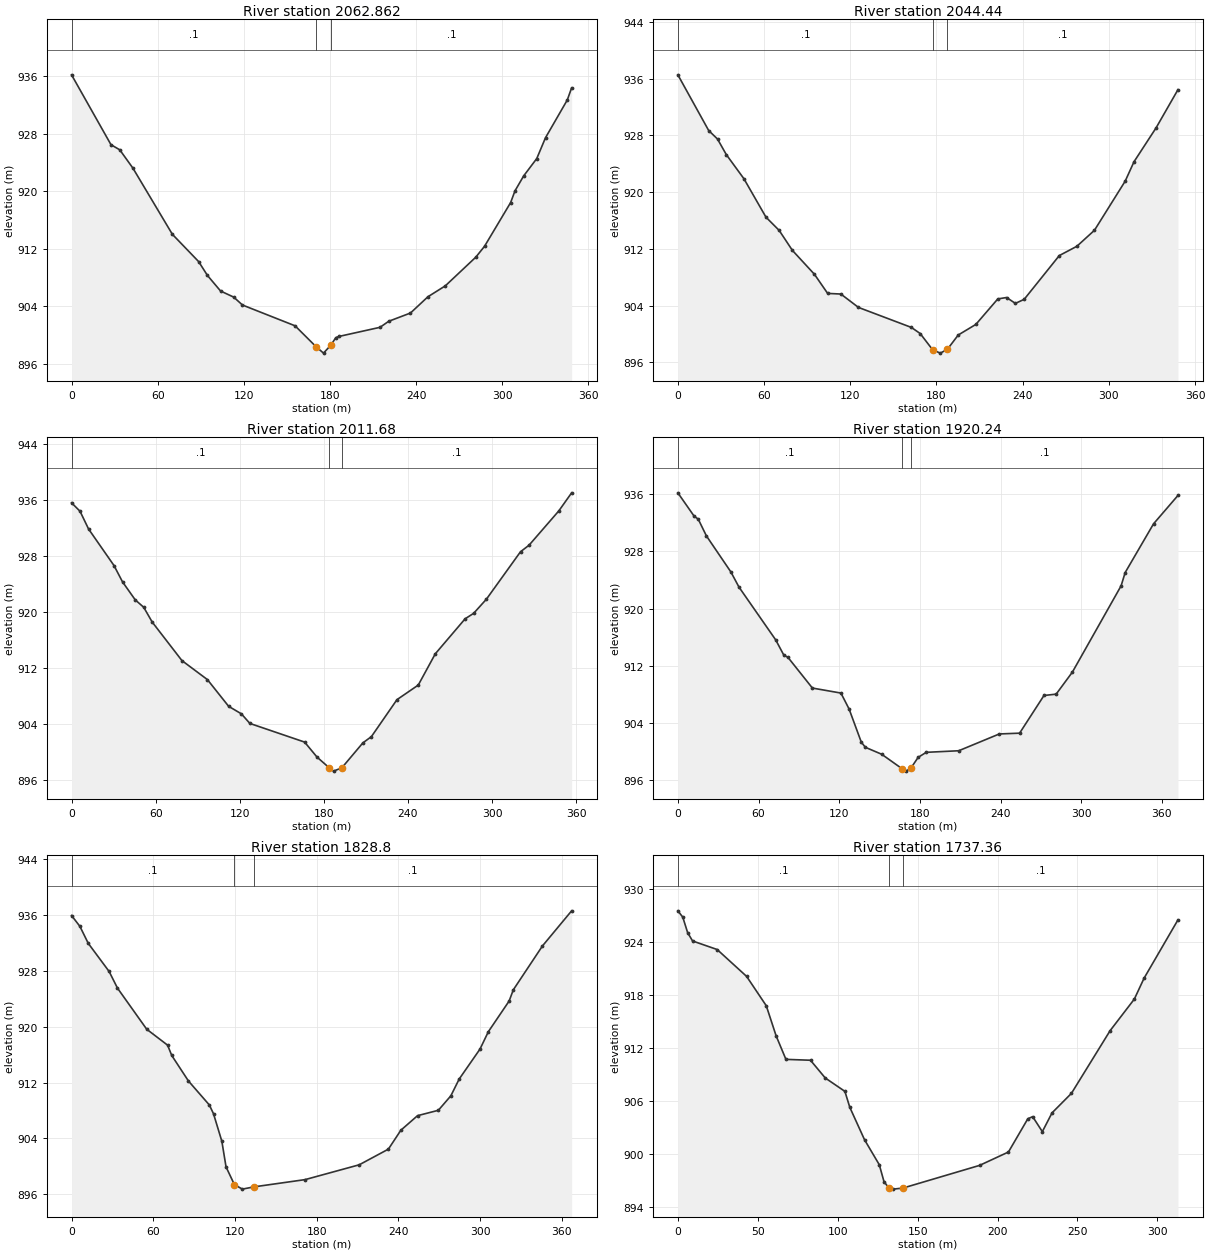
Type RM Length L Ch R = 1 ,2062.862,16.44,18.42,25.56
XS GIS Cut Line= 6
     627984.1332    4335096.7332     627847.7485    4335004.1543
      627842.986    4335006.5356     627829.2276     4335004.948
     627824.4651     4335009.446      627675.893    4334956.5038
#Sta/Elev= 30
       0  936.21   27.47  926.49   33.58  925.78   42.74  923.23   70.21  914.03
   88.52  910.23   94.63  908.31  103.79  906.14  112.94  905.29  119.05  904.19
  155.68   901.3  170.16  898.42  175.48   897.5  180.63  898.62  184.01  899.64
   186.2  899.82  214.83  901.09   220.9  901.93  236.06  903.08   248.2  905.34
  260.33  906.86  281.56  910.85  287.63  912.36  305.82  918.45  308.86  920.08
  314.92  922.16  324.02  924.57  330.09  927.46  345.26  932.71  348.29   934.4
#Mann= 3 , 0 , 0
       0      .1       0  170.16      .1       0  180.63      .1       0
Bank Sta=170.16,180.63
XS Rating Curve= 0 ,0
Exp/Cntr=0.3,0.1

Type RM Length L Ch R = 1 ,2044.44 ,27.69,32.76,38.52
XS GIS Cut Line= 5
     627988.4547    4335095.2339     627849.6262    4334989.0421
     627839.1619    4334987.6266     627832.8119    4334985.2983
     627685.7708    4334933.3086
#Sta/Elev= 30
       0  936.56   21.46   928.7    27.6   927.5   33.73   925.3      46  921.89
   61.33  916.47   70.53   914.6   79.73  911.78   95.06  908.41  104.26  905.71
  113.46  905.62  125.72  903.73  162.52  900.91  168.65  900.05  177.43  897.73
  182.71  897.28   187.6  897.82  195.17  899.84   207.4  901.33  222.69  904.93
  228.81  905.13  234.92   904.3  241.04  904.87   265.5  911.05  277.73  912.36
  289.97  914.62  311.37  921.56  317.49  924.29  332.78  929.05  348.07  934.46
#Mann= 3 , 0 , 0
       0      .1       0  177.43      .1       0   187.6      .1       0
Bank Sta=177.43,187.6
XS Rating Curve= 0 ,0
Exp/Cntr=0.3,0.1

Type RM Length L Ch R = 1 ,2011.68 ,96.35,91.44,88.82
XS GIS Cut Line= 4
     628012.7964    4335075.1256     627882.3509    4334992.3895
     627856.2682    4334956.6468     627746.0959    4334843.3501
#Sta/Elev= 30
       0  935.56    6.06  934.35   12.12  931.83   30.29  926.61   36.35  924.29
   45.43  921.72   51.49  920.66   57.55  918.55   78.75  913.06   96.92  910.35
  112.07  906.54  121.15  905.47  127.21   904.1  166.27  901.44  175.12   899.3
  183.97  897.75  186.92   897.3  192.82  897.77  207.84  901.33  213.91  902.22
  232.15  907.49  247.34  909.57   259.5  914.03  280.77  919.02  286.85   919.8
  295.97  921.82  320.28  928.58  326.36  929.51  347.63  934.41  356.75  936.98
#Mann= 3 , 0 , 0
       0      .1       0  183.97      .1       0  192.82      .1       0
Bank Sta=183.97,192.82
XS Rating Curve= 0 ,0
Exp/Cntr=0.3,0.1

Type RM Length L Ch R = 1 ,1920.24 ,101.6,91.44,67.64
XS GIS Cut Line= 5
     628038.1965    4335050.7838     627948.4426    4334924.8463
     627930.2873    4334909.0721     627906.0992    4334874.3968
       627778.04    4334794.4374
#Sta/Elev= 30
       0  936.19   12.13  932.92   15.16  932.51   21.23  930.17   39.42  925.13
   45.48     923   72.78  915.62   78.84  913.48   81.87  913.18  100.07  908.88
  121.29  908.18  127.36  905.95  136.45  901.31  139.49  900.59  151.62  899.62
  166.67  897.61  169.68  897.26  173.26  897.66   178.7  899.18  184.74  899.89
   208.9  900.11  239.09  902.46  254.19  902.57  272.31  907.84  281.37  908.03
  293.44  911.11  329.68  923.18   332.7  925.04  353.83  931.86  371.95  935.82
#Mann= 3 , 0 , 0
       0      .1       0  166.67      .1       0  173.26      .1       0
Bank Sta=166.67,173.26
XS Rating Curve= 0 ,0
Exp/Cntr=0.3,0.1

Type RM Length L Ch R = 1 ,1828.8  ,85.97,91.44,83.8
XS GIS Cut Line= 5
     628123.3219    4334842.0625     628004.5204    4334855.7128
      627978.271    4334854.9581     627952.6688    4334856.3215
     627779.3629    4334765.3331
#Sta/Elev= 30
       0   935.9    6.13  934.35   12.26  931.92    27.6  927.89   33.73  925.51
   55.19  919.63   70.52  917.35   73.59  915.87   85.85  912.22  101.19  908.79
  104.25  907.53  110.38  903.59  113.45  899.93  119.58   897.4  125.42  896.75
  134.17  897.08  171.48  898.11  211.24  900.23  232.65  902.47  241.83  905.18
  254.06  907.26  269.35  908.03  278.53   910.1  284.64   912.5  299.94  916.79
  306.05  919.27  321.34  923.67   324.4  925.27  345.81  931.55  367.22  936.57
#Mann= 3 , 0 , 0
       0      .1       0  119.58      .1       0  134.17      .1       0
Bank Sta=119.58,134.17
XS Rating Curve= 0 ,0
Exp/Cntr=0.3,0.1

Type RM Length L Ch R = 1 ,1737.36 ,93.47,91.44,85.07
XS GIS Cut Line= 6
     628127.2907    4334764.0102     628001.4837    4334771.4174
     627992.6388    4334770.5727     627971.3305    4334771.7245
     627936.4457     4334777.956     627816.4046    4334761.3644
#Sta/Elev= 30
       0  927.56    3.07  926.85    6.15  925.07    9.22  924.14   24.59  923.17
   43.03  920.12   55.33  916.79   61.48  913.38   67.62  910.71   82.99  910.61
   92.21   908.6  104.51  907.08  107.58  905.27   116.8  901.59  126.02  898.76
  128.99  896.83  131.95  896.15  134.91  895.99  141.01  896.12  188.73  898.68
  206.83   900.2  218.95  903.97  221.98  904.21  228.04  902.51   234.1  904.64
  246.22  906.85  270.45  913.97   285.6  917.55  291.66  919.91  312.87  926.53
#Mann= 3 , 0 , 0
       0      .1       0  131.95      .1       0  141.01      .1       0
Bank Sta=131.95,141.01
XS Rating Curve= 0 ,0
Exp/Cntr=0.3,0.1

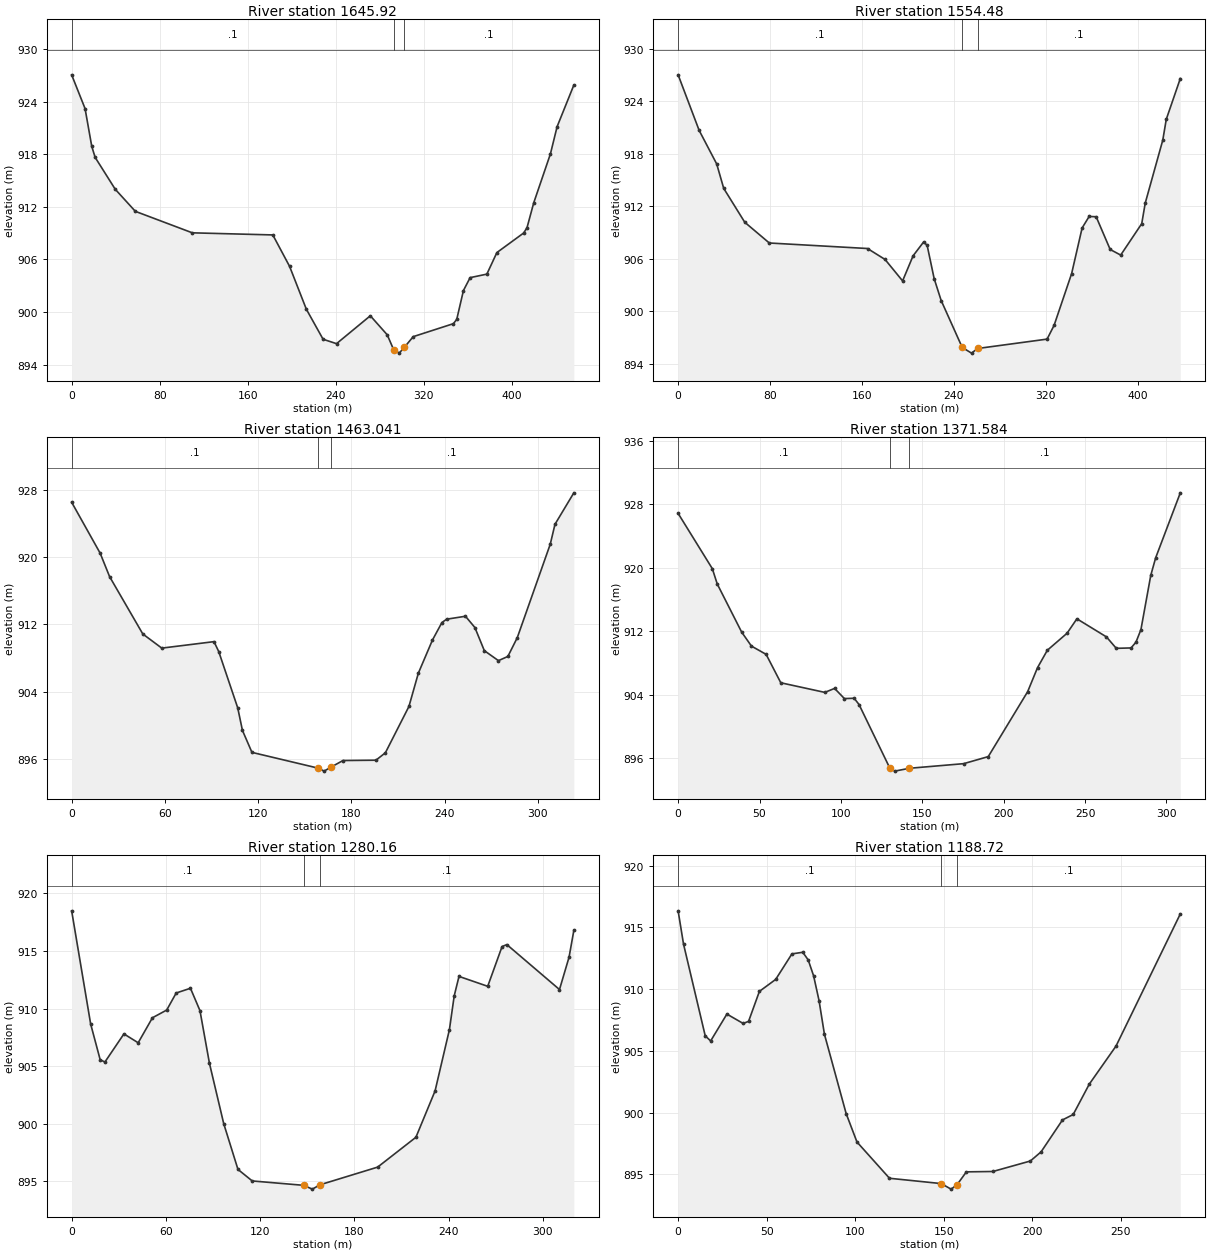
Type RM Length L Ch R = 1 ,1645.92 ,81.87,91.44,84.98
XS GIS Cut Line= 6
     628275.4576    4334627.7495     628040.9034     4334666.213
      627991.247    4334682.3407     627980.3968    4334683.8486
     627970.7831    4334684.5016     627829.6338    4334721.6768
#Sta/Elev= 30
       0  927.06   12.19  923.21   18.28   918.9   21.33  917.65   39.61  914.01
    57.9  911.49   109.7  909.04  182.84   908.8  198.07  905.22  213.31  900.33
  228.55   896.9  240.76   896.4  271.47  899.58  286.83  897.41  292.64  895.72
  297.73  895.32  302.36  895.98  310.49   897.2  346.98  898.68  350.02  899.17
   356.1  902.46  362.18  903.93  377.39  904.33  386.51  906.79  410.84  909.02
  413.88  909.62  419.96  912.45  435.16  918.04  441.25  921.15  456.45  925.89
#Mann= 3 , 0 , 0
       0      .1       0  292.64      .1       0  302.36      .1       0
Bank Sta=292.64,302.36
XS Rating Curve= 0 ,0
Exp/Cntr=0.3,0.1

Type RM Length L Ch R = 1 ,1554.48 ,92.53,91.44,87.43
XS GIS Cut Line= 6
     628260.1118    4334602.7905      628009.818    4334610.4357
      627990.768    4334617.8441      627968.543    4334614.6691
     627965.7913    4334608.7424      627830.163    4334586.9154
#Sta/Elev= 30
       0  927.03   18.32  920.68   33.59  916.85    39.7  914.06   58.02  910.19
    79.4  907.82   164.9  907.19  180.17  905.94  195.44  903.49   204.6  906.36
  213.77  907.94  216.82  907.55  222.93  903.75  229.03  901.25  247.36  895.89
  255.45  895.24   260.8  895.77  321.24  896.84  327.34  898.41  342.61  904.32
  351.76  909.54  357.87  910.85  363.98  910.82  376.19  907.08  385.34  906.44
  403.66  910.03  406.71  912.38  421.98  919.57  425.03  921.95  437.24  926.61
#Mann= 3 , 0 , 0
       0      .1       0  247.36      .1       0   260.8      .1       0
Bank Sta=247.36,260.8
XS Rating Curve= 0 ,0
Exp/Cntr=0.3,0.1

Type RM Length L Ch R = 1 ,1463.041,76.92,91.46,88.48
XS GIS Cut Line= 4
     628137.0803    4334474.4673     627986.4593    4334524.6121
     627983.4089    4334526.7046      627830.163    4334575.0091
#Sta/Elev= 30
       0  926.52   18.32  920.47   24.42  917.67   45.79  910.85      58  909.17
   91.59  909.94   94.64  908.76  106.85  902.07   109.9  899.38  116.01  896.77
  158.75  894.89  162.45  894.54  166.63  894.99  174.57   895.8   195.8  895.84
  201.86  896.72  217.02  902.23  223.08  906.19  232.18  910.14  238.24  912.21
  241.27  912.61   253.4  912.96  259.46  911.62  265.53  908.87  274.62  907.68
  280.68  908.18  286.75  910.42  307.97  921.54     311   923.9  323.13  927.64
#Mann= 3 , 0 , 0
       0      .1       0  158.75      .1       0  166.63      .1       0
Bank Sta=158.75,166.63
XS Rating Curve= 0 ,0
Exp/Cntr=0.3,0.1

Type RM Length L Ch R = 1 ,1371.584,94.87,91.42,62.72
XS GIS Cut Line= 4
     628126.4969    4334418.9047      628012.168    4334444.4961
     628006.4078    4334452.4973     627831.4859    4334500.9257
#Sta/Elev= 30
       0  926.85   21.03  919.88   24.03  917.96   39.05  911.89   45.06  910.13
   54.07  909.09   63.09  905.51   90.12   904.3   96.13   904.8  102.14  903.52
  108.15  903.56  111.15  902.77  130.04  894.77  133.07  894.38  142.14  894.74
  175.42  895.32  190.54  896.21  214.74  904.39  220.79  907.41  226.84  909.61
  238.94  911.75  244.99  913.57  263.14  911.29  269.19  909.85  278.27   909.9
  281.29  910.63  284.32   912.2  290.37  919.04  293.39  921.26  308.52  929.44
#Mann= 3 , 0 , 0
       0      .1       0  130.04      .1       0  142.14      .1       0
Bank Sta=130.04,142.14
XS Rating Curve= 0 ,0
Exp/Cntr=0.3,0.1

Type RM Length L Ch R = 1 ,1280.16 ,47.88,91.44,116.78
XS GIS Cut Line= 6
     628114.5907    4334352.7587     627996.8304    4334360.3915
     627977.2146    4334374.4761     627972.5361    4334387.5165
     627960.8801    4334408.0166      627830.163    4334458.5922
#Sta/Elev= 30
       0  918.48    12.1  908.66   18.16  905.56   21.18  905.36   33.28   907.8
   42.36  907.03   51.44   909.2   60.52  909.87   66.57  911.35   75.65  911.76
    81.7  909.82   87.75  905.24   96.83  900.01   105.9  896.04  114.98  895.04
   147.7  894.66  153.24  894.33   158.2  894.71  194.83  896.24   219.2  898.83
  231.39  902.85  240.53  908.17  243.58   911.1  246.63  912.79  264.91  911.93
  274.05  915.38   277.1  915.55  310.61  911.65  316.71  914.46  319.75  916.78
#Mann= 3 , 0 , 0
       0      .1       0   147.7      .1       0   158.2      .1       0
Bank Sta=147.7,158.2
XS Rating Curve= 0 ,0
Exp/Cntr=0.3,0.1

Type RM Length L Ch R = 1 ,1188.72 ,101.08,91.44,75.17
XS GIS Cut Line= 6
     628113.5323    4334345.3504      627988.914    4334330.2784
     627973.3565    4334322.1821     627965.4225    4334314.3989
     627956.4272    4334307.1885     627853.1818    4334250.1002
#Sta/Elev= 30
       0  916.35    3.06  913.65   15.31  906.22   18.37   905.8   27.55  907.98
   36.74  907.22    39.8  907.39   45.92  909.82   55.11  910.79   64.29  912.86
   70.42  912.99   73.48  912.37   76.54  911.08    79.6  909.08   82.66  906.34
   94.91  899.92  101.03  897.61   119.4  894.67  148.62  894.24  154.18  893.79
  157.44  894.12  162.83  895.19  177.81  895.22  198.98  896.07  205.03  896.81
  217.13   899.4  223.18  899.84  232.26   902.3  247.38  905.39  283.68   916.1
#Mann= 3 , 0 , 0
       0      .1       0  148.62      .1       0  157.44      .1       0
Bank Sta=148.62,157.44
XS Rating Curve= 0 ,0
Exp/Cntr=0.3,0.1

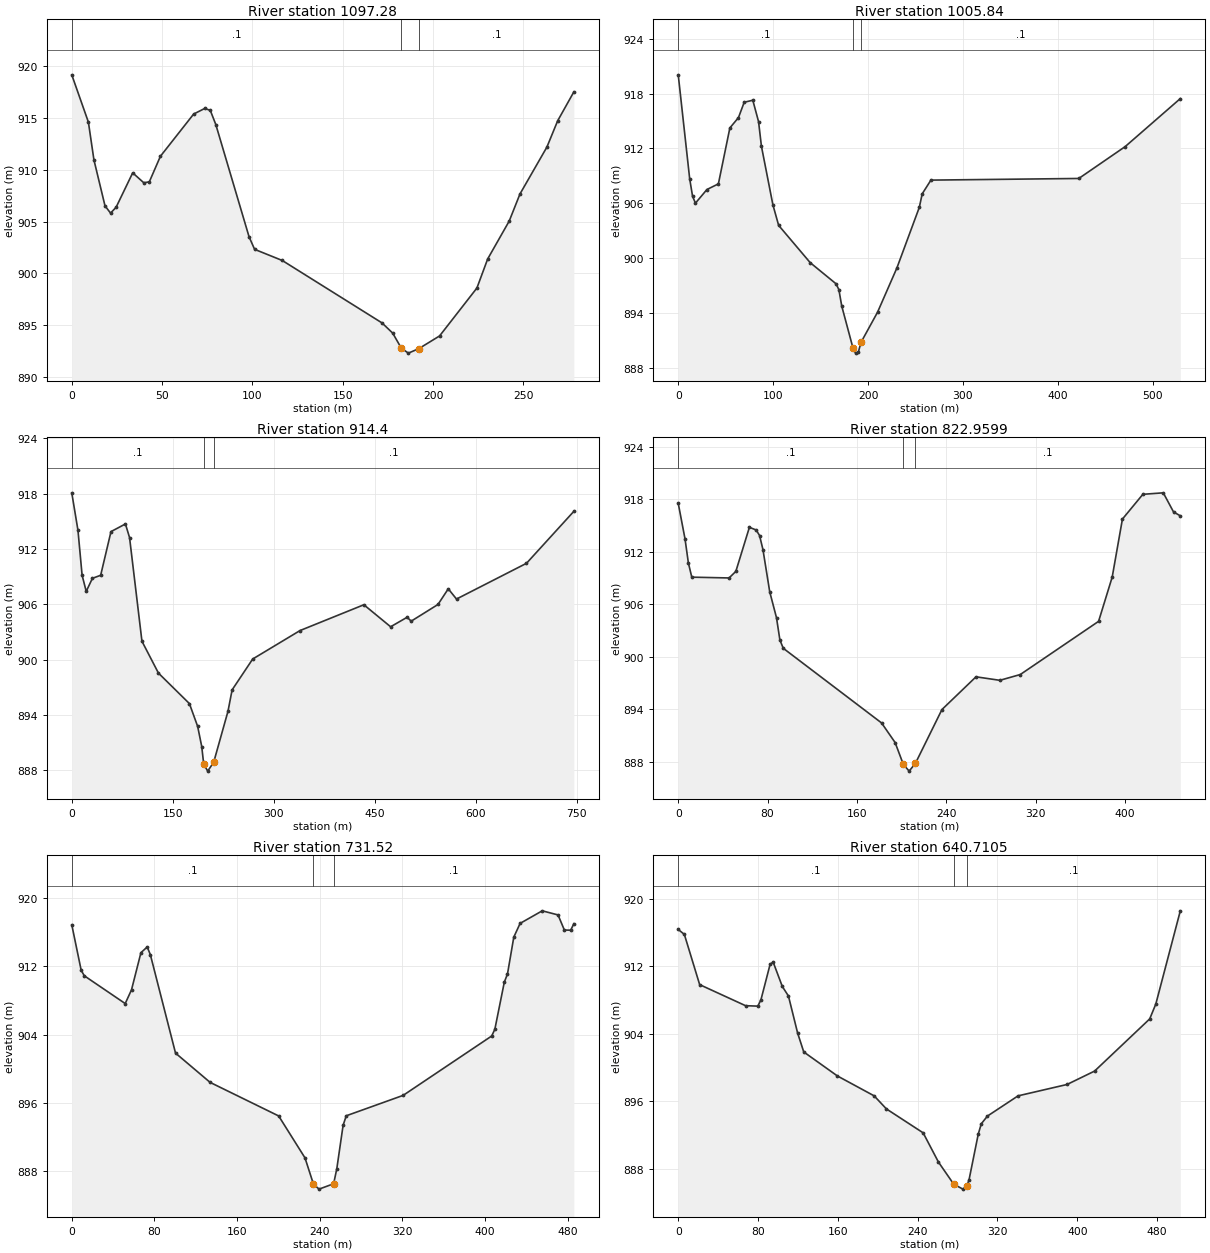
Type RM Length L Ch R = 1 ,1097.28 ,76.47,91.44,99.25
XS GIS Cut Line= 4
     628129.4074    4334310.4253     627976.4539    4334225.8014
     627943.1707    4334235.1414     627875.4068    4334224.7001
#Sta/Elev= 30
       0  919.18     9.2  914.61   12.27  910.96    18.4  906.52   21.47  905.82
   24.53  906.38   33.73  909.71   39.87  908.75   42.93  908.84   49.07  911.31
   67.47  915.39    73.6  915.93   76.67  915.75   79.73  914.38   98.13  903.54
   101.2  902.32  116.54  901.24  171.74  895.21  177.68  894.22  182.43  892.77
  186.33  892.29  192.09  892.72  203.61  893.95  224.28  898.58  230.24  901.39
  242.16  905.05  248.12  907.67  263.03   912.2  268.99  914.74  277.94  917.53
#Mann= 3 , 0 , 0
       0      .1       0  182.43      .1       0  192.09      .1       0
Bank Sta=182.43,192.09
XS Rating Curve= 0 ,0
Exp/Cntr=0.3,0.1

Type RM Length L Ch R = 1 ,1005.84 ,89.73,91.44,91.46
XS GIS Cut Line= 5
     628170.6824    4334231.0501     628008.4562    4334156.9543
     627993.4356    4334148.8663     627946.0203    4334126.2614
     627675.3814    4334050.0748
#Sta/Elev= 30
       0  920.05   12.09  908.65   15.11  906.76   18.14  906.01   30.23   907.5
   42.32  908.12   54.41  914.24   63.48  915.37   69.52  917.05   78.59  917.27
   84.64  914.93   87.66  912.24   99.75  905.83   105.8  903.58  139.05   899.5
  166.26  897.19  169.28  896.55   172.3  894.75  184.03   890.2  186.88   889.6
  189.72  889.68  192.56  890.77     210  894.07  230.43  898.92  254.05  905.55
   257.1  907.03  266.27  908.53  422.13  908.71  471.03   912.2  529.09  917.45
#Mann= 3 , 0 , 0
       0      .1       0  184.03      .1       0  192.56      .1       0
Bank Sta=184.03,192.56
XS Rating Curve= 0 ,0
Exp/Cntr=0.3,0.1

Type RM Length L Ch R = 1 ,914.4   ,81.67,91.44,103.58
XS GIS Cut Line= 4
      628207.195    4334181.8375     628049.5809    4334075.6712
     628026.3862    4334062.4869     627510.2811    4333946.8871
#Sta/Elev= 30
       0   918.1     9.2  914.03   15.33  909.16   21.46   907.4   30.65  908.82
   42.91  909.15   58.24  913.89   79.69  914.72   85.82  913.24  104.21  901.99
  128.73  898.53  174.71  895.22  186.97  892.74     193  890.56  195.96  888.64
  201.89  887.89  210.79  888.86     232  894.39  238.12  896.71  268.69  900.06
     339  903.15  433.78  905.95  473.52  903.56  497.98  904.59  504.09  904.17
  543.83  905.98  559.12  907.68  571.35  906.57  675.29  910.45  745.61  916.09
#Mann= 3 , 0 , 0
       0      .1       0  195.96      .1       0  210.79      .1       0
Bank Sta=195.96,210.79
XS Rating Curve= 0 ,0
Exp/Cntr=0.3,0.1

Type RM Length L Ch R = 1 ,822.9599,103.77,91.44,81.36
XS GIS Cut Line= 5
     628223.4669    4334158.1573     628096.1889    4334007.4655
     628093.7296    4334001.2064     628082.8151    4333988.2454
     627966.2914     4333791.444
#Sta/Elev= 30
       0  917.56    6.07   913.5     9.1  910.73   12.14  909.12   45.52  909.03
   51.59  909.78   63.73  914.82    69.8  914.51   72.83  913.88   75.87  912.27
   81.93  907.45      88  904.48   91.04  901.94   94.07  900.99  182.08  892.46
  194.22  890.22  201.54  887.73   206.8  886.95  212.45  887.85  236.17  893.99
  266.66  897.73  288.01  897.33  306.31  897.99  376.44  904.07  388.64  909.13
  397.79  915.76  416.09  918.59  434.38  918.76  443.53  916.58  449.63  916.13
#Mann= 3 , 0 , 0
       0      .1       0  201.54      .1       0  212.45      .1       0
Bank Sta=201.54,212.45
XS Rating Curve= 0 ,0
Exp/Cntr=0.3,0.1

Type RM Length L Ch R = 1 ,731.52  ,75.24,90.81,100.22
XS GIS Cut Line= 6
     628320.3046    4334101.0072     628200.4967    4333951.3014
     628170.7974    4333941.3933     628155.9295    4333934.6818
     628144.9552    4333933.1576     627974.2289    4333770.8065
#Sta/Elev= 30
       0  916.88    9.13  911.54   12.17   910.9   51.74  907.65   57.83  909.26
   66.96  913.61   73.05  914.28   76.09  913.37  100.44  901.85  133.92  898.42
  200.28  894.49  225.77  889.58  233.93  886.52  239.37  885.92   253.5  886.55
  256.56   888.3  262.68   893.4  265.74  894.51  320.82   896.9  406.49  903.85
  409.55  904.63  418.73  910.16  421.79  911.11  427.91  915.43  434.03  917.04
  455.44  918.51  470.74  918.03  476.86  916.26  482.98  916.24  486.04     917
#Mann= 3 , 0 , 0
       0      .1       0  233.93      .1       0   253.5      .1       0
Bank Sta=233.93,253.5
XS Rating Curve= 0 ,0
Exp/Cntr=0.3,0.1

Type RM Length L Ch R = 1 ,640.7105,92,92.07,92.45
XS GIS Cut Line= 2
     628391.7423    4334093.0696     628074.2416    4333702.5439
#Sta/Elev= 30
       0  916.39    6.14   915.8   21.48  909.84   67.52  907.34   79.79  907.29
   82.86  908.02   92.07  912.24   95.14  912.52  104.34  909.62  110.48  908.49
  119.69  904.09  125.83  901.85  159.58     899  196.41  896.64  208.69  895.09
  245.52  892.25  260.86  888.78   276.2  886.15  285.41  885.57   289.3  885.94
  291.55  886.69  300.76   892.1  303.83  893.33  309.96  894.24  340.65  896.64
  389.76  897.99  417.38  899.58  472.62  905.77  478.76  907.54  503.31   918.6
#Mann= 3 , 0 , 0
       0      .1       0   276.2      .1       0   289.3      .1       0
Bank Sta=276.2,289.3
XS Rating Curve= 0 ,0
Exp/Cntr=0.3,0.1