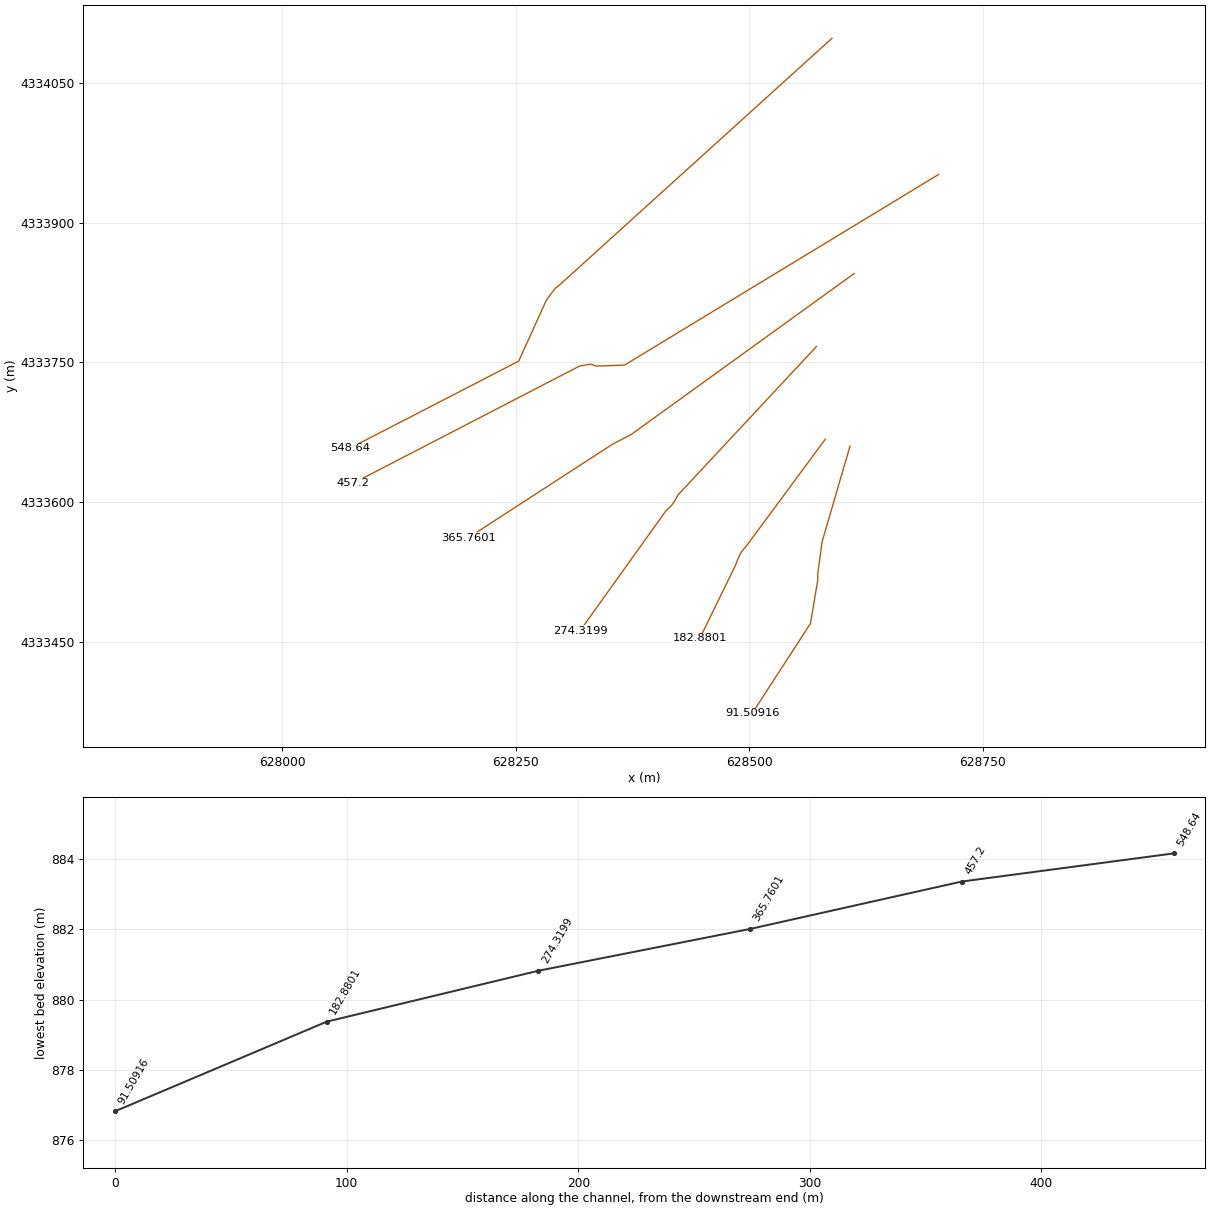
HEC-RAS study SnyderRun.prj: SnyderRun

--- SnyderRun.g01 (geometry) --- (continued)

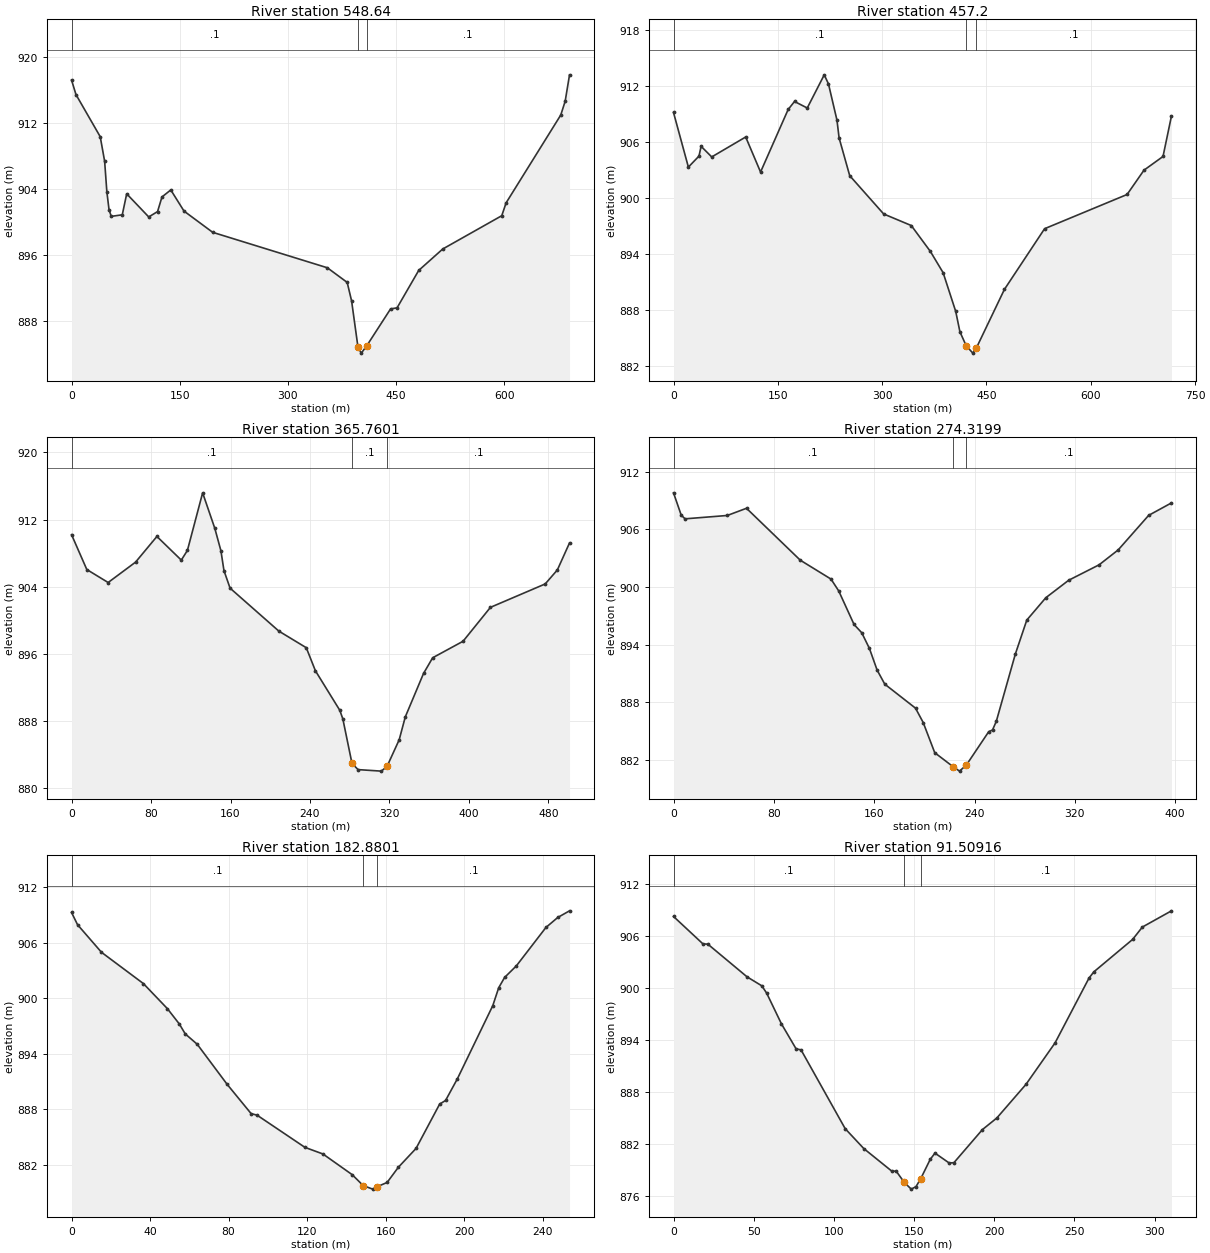
Type RM Length L Ch R = 1 ,548.64  ,106.45,91.44,79
XS GIS Cut Line= 6
     628588.5926    4334097.8321     628296.4216    4333832.7271
     628292.0344    4333829.3944     628282.8749    4333817.0637
     628253.1312    4333751.4216     628072.6541    4333658.0938
#Sta/Elev= 30
       0   917.2    6.12  915.45   39.76  910.35   45.87  907.38   48.93   903.7
   51.99  901.51   55.05  900.71   70.34   900.9   76.46  903.44  107.04  900.64
  119.27  901.29  125.39  903.06  137.62  903.91  155.97  901.35  195.73  898.78
  354.76  894.49  382.28  892.72   388.4  890.48  397.27  884.87  401.86  884.16
  409.56  885.07  442.45  889.51  451.46  889.64  481.49  894.17  514.79  896.76
  596.67  900.79  602.73  902.35  678.54  912.98  684.61  914.64  690.67  917.84
#Mann= 3 , 0 , 0
       0      .1       0  397.27      .1       0  409.56      .1       0
Bank Sta=397.27,409.56
XS Rating Curve= 0 ,0
Exp/Cntr=0.3,0.1

Type RM Length L Ch R = 1 ,457.2   ,77.81,91.44,94.87
XS GIS Cut Line= 6
     628702.8929    4333951.7819     628366.4657     4333747.136
      628336.409    4333746.0776     628330.2534    4333748.2238
     628318.4414    4333746.1713     628075.5116    4333620.2054
#Sta/Elev= 30
       0  909.18   21.37  903.32   36.63   904.5   39.68  905.55   54.95  904.41
  103.79  906.55  125.16  902.79  164.84   909.5     174  910.36  192.31  909.66
  216.73  913.22  222.84  912.24  235.05  908.35   238.1  906.45  253.36   902.4
   302.2  898.29  341.89  897.05  369.36  894.27  387.68  891.99  405.81  887.83
  411.83  885.65  420.85  884.15  430.38  883.36  435.41   883.9  475.83   890.2
   533.6  896.71  652.18  900.38   676.5  902.99  703.87  904.46  716.03  908.81
#Mann= 3 , 0 , 0
       0      .1       0  420.85      .1       0  435.41      .1       0
Bank Sta=420.85,435.41
XS Rating Curve= 0 ,0
Exp/Cntr=0.3,0.1

Type RM Length L Ch R = 1 ,365.7601,80.45,91.44,97.81
XS GIS Cut Line= 4
     628612.4052    4333845.4191     628373.7439    4333672.7846
     628353.3805    4333662.1021     628199.3369    4333561.9969
#Sta/Elev= 30
       0  910.19   15.34  906.04   36.82  904.49   64.43  906.92   85.91  909.98
  110.46  907.16  116.59  908.31  131.94  915.18  144.21  910.94  150.35  908.27
  153.41  905.91  159.55  903.82  208.64   898.7  236.26  896.72  245.46  893.97
  270.01  889.26  273.08  888.23  282.28  882.93  288.42  882.19   311.8  882.01
  317.55  882.57   329.8  885.75  335.92  888.47  354.29  893.65  363.48  895.52
   394.1  897.49  421.65  901.53  476.77  904.32  489.01  905.99  501.26  909.21
#Mann= 3 , 0 , 0
       0      .1       0  282.28      .1       0  317.55      .1       0
Bank Sta=282.28,317.55
XS Rating Curve= 0 ,0
Exp/Cntr=0.3,0.1

Type RM Length L Ch R = 1 ,274.3199,90.06,91.44,97.26
XS GIS Cut Line= 6
     628571.9768    4333767.1023     628423.8131    4333607.9055
      628419.988    4333600.9983     628416.8967    4333596.6525
     628410.7955    4333590.7605     628319.0346    4333462.3017
#Sta/Elev= 30
       0  909.82    6.13   907.5    9.19  907.11   42.88  907.46    58.2  908.21
  101.08   902.8  125.59  900.83  131.71   899.6  143.96   896.1  150.09  895.24
  156.22   893.6  162.34  891.35  168.47  889.88  192.97  887.38   199.1  885.88
  208.29  882.74  222.74   881.3  228.04  880.82  233.53  881.46  251.33  884.93
  254.37  885.11   257.4  886.02  272.58  893.03  281.69  896.56  296.87  898.89
  315.08  900.71  339.37  902.32  354.55  903.87  378.84  907.47  397.05  908.77
#Mann= 3 , 0 , 0
       0      .1       0  222.74      .1       0  233.53      .1       0
Bank Sta=222.74,233.53
XS Rating Curve= 0 ,0
Exp/Cntr=0.3,0.1

Type RM Length L Ch R = 1 ,182.8801,78.85,91.37,94.87
XS GIS Cut Line= 6
     628581.5018    4333667.6188     628498.2273    4333554.7683
     628491.3576    4333546.2994     628488.3843    4333540.2399
     628485.2583    4333532.2516     628447.0932     4333453.835
#Sta/Elev= 30
       0  909.26    3.05  907.94   15.24  904.96   36.59  901.58   48.78  898.88
   54.88  897.22   57.93  896.14   64.03  895.02   79.27  890.69   91.47  887.53
   94.52  887.36  118.91  883.88  128.05  883.17  142.98  880.93  148.53  879.76
   153.4  879.37  155.65  879.63  160.76  880.09  166.48  881.73   175.5  883.77
  187.53  888.56  190.54  888.95  196.55  891.29   214.6   899.2  217.61  901.13
  220.61  902.24  226.63   903.5  241.66  907.64  247.68  908.72  253.69  909.44
#Mann= 3 , 0 , 0
       0      .1       0  148.53      .1       0  155.65      .1       0
Bank Sta=148.53,155.65
XS Rating Curve= 0 ,0
Exp/Cntr=0.3,0.1

Type RM Length L Ch R = 1 ,91.50916,86.62,91.51,81.56
XS GIS Cut Line= 6
     628607.9602    4333660.2104     628578.0262    4333557.4498
     628573.3894    4333523.0217     628573.4459    4333516.5628
     628565.6069    4333469.8912      628503.185    4333373.4015
#Sta/Elev= 30
       0  908.24   18.35  905.08   21.41  905.05   45.87  901.28   55.04  900.25
    58.1   899.4   67.28  895.87   76.45  892.98   79.51  892.87  107.03  883.79
  118.61   881.5  135.98  878.91  138.88  878.88  143.92  877.59  148.23  876.82
  151.19  877.11  154.15  878.03  160.06  880.25  163.02  880.97  171.89  879.83
  174.85  879.87   192.6  883.68   201.6  885.02  219.75  888.89  237.89  893.67
  259.06  901.14  262.09  901.86  286.28   905.6  292.33  907.02  310.48  908.89
#Mann= 3 , 0 , 0
       0      .1       0  143.92      .1       0  154.15      .1       0
Bank Sta=143.92,154.15
XS Rating Curve= 0 ,0
Exp/Cntr=0.3,0.1
LCMann Table=0

Chan Stop Cuts=-1
Use User Specified Reach Order=0
Composite Channel Slope=5